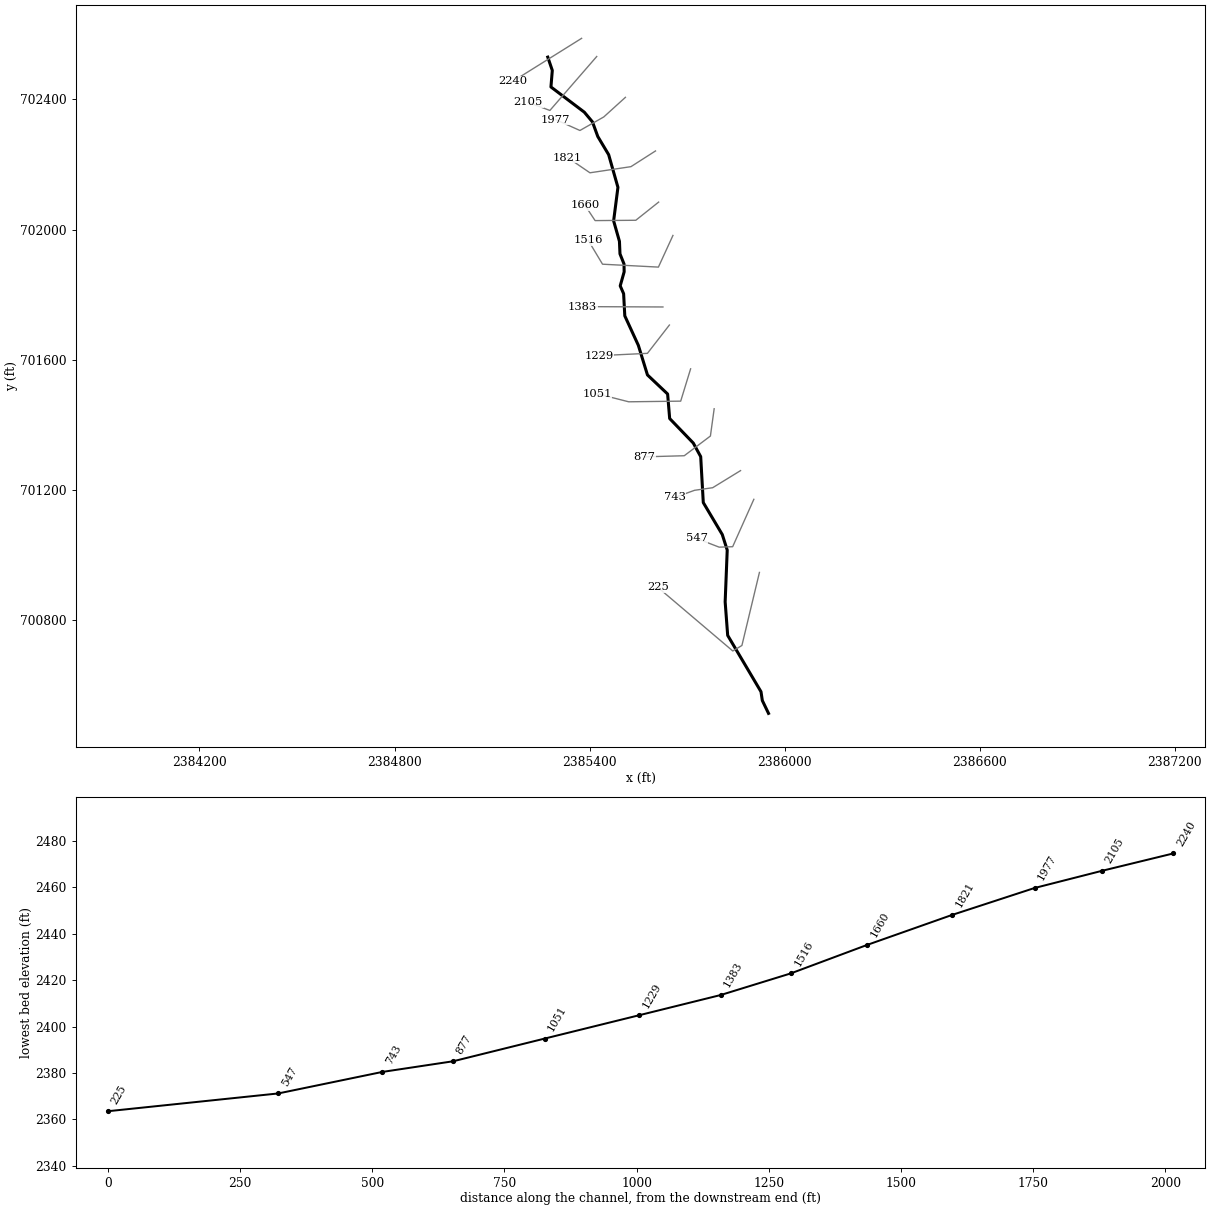
--- DRKFK_2T2.prj (project) ---

Proj Title=DRKFK_2T2
Current Plan=p01
Default Exp/Contr=0,0
English Units
Geom File=g01
Flow File=f01
Plan File=p01
BEGIN DESCRIPTION:
----------MODEL BY WOOD PLC 2022----------
AFH study
Randolph County, WV
HEC-RAS Version: RAS 6.2
Vertical Datum: NAVD88
Projection: NAD 1983 StatePlane West Virginia S FIPS 4702 (US Feet)
Terrain: 1-meter LIDAR (FEMA Region III 3DEP collected 2016-2018)
Land Use: 2019 NLCD
Hydrologic Method:
WV SIR2010-5033 regression equations
Additional Model Notes:
None
END DESCRIPTION:
DSS Export Rating Curves= 0
DSS Export Rating Curve Sorted= 0
DSS Export Volume Flow Curves= 0
DXF OffsetX= 0
DXF OffsetY= 0
DXF ScaleX= 0
DXF ScaleY= 0

--- DRKFK_2T2.p01 (plan) ---

Plan Title=Floodplain
Program Version=6.20
Short Identifier=Floodplain
Geom File=g01
Flow File=f01
Subcritical Flow
K Sum by GR= 0
Std Step Tol= 0.01
Critical Tol= 0.01
Num of Std Step Trials= 20
Max Error Tol= 0.3
Flow Tol Ratio= 0.001
Split Flow NTrial= 30
Split Flow Tol= 0.02
Split Flow Ratio= 0.02
Log Output Level= 0
Friction Slope Method= 1
Unsteady Friction Slope Method= 2
Unsteady Bridges Friction Slope Method= 1
Parabolic Critical Depth
Global Vel Dist= 0 , 0 , 0
Global Log Level= 0
CheckData=True
Encroach Param=-1 ,0,0, 0
Mapping Interval=1HOUR
Computation Time Step Use Courant=        0
Computation Time Step Use Time Series=    0
Computation Time Step Count To Double=0
Computation Time Step Max Doubling=0
Computation Time Step Max Halving=0
Computation Time Step Residence Courant=0
Run HTab= 0
Run UNet= 0
Run Sediment= 0
Run PostProcess= 0
Run WQNet= 0
Run RASMapper=-1
UNET Theta= 0
UNET Theta Warmup= 0
UNET ZTol= 0
UNET ZSATol= 0
UNET MxIter= 0
UNET Max Iter WO Improvement= 0
UNET MaxInSteps= 0
UNET DtIC= 0
UNET DtMin= 0
UNET MaxCRTS= 0
UNET WFStab= 0
UNET SFStab= 0
UNET WFX= 1
UNET SFX= 1
UNET Gravity=32.174
UNET 1D Methodology=Finite Difference
UNET DSS MLevel= 1
UNET Pardiso=0
UNET DZMax Abort= 0
UNET Use Existing IB Tables= 0
UNET Froude Reduction=False
UNET Froude Limit= 0
UNET Froude Power= 0
UNET D1 Cores= 0
UNET WindReference=Eulerian
UNET WindDragFormulation=Hsu (1988)
UNET D2 Coriolis=0
UNET D2 Cores= 0
UNET D2 Theta= 1
UNET D2 Theta Warmup= 1
UNET D2 Z Tol= 0.01
UNET D2 Volume Tol= 0.01
UNET D2 Max Iterations= 20
UNET D2 Equation= 0
UNET D2 RampUpFraction=0.1
UNET D2 TimeSlices= 1
UNET D2 Turbulence Formulation=Non-Conservative (original)
UNET D2 Eddy Viscosity=0.3
UNET D2 Transverse Eddy Viscosity=0.1
UNET D2 Smagorinsky Mixing=0
UNET D2 BCVolumeCheck=0
UNET D2 Cores=0
UNET D2 SolverType=PARDISO (Direct)
UNET D2 Minimum Iterations= 2147483647
UNET D2 Maximum Iterations= 2147483647
UNET D2 Restart Number= 10
UNET D2 Relaxation Coeff=1.3
UNET D2 SOR Precondition Iterations= 10
UNET D2 ILUT Maximum Fill= 8
UNET D2 ILUT Tolerance=1E-08
UNET D1D2 MaxIter= 0
UNET D1D2 ZTol=0.01
UNET D1D2 QTol=0.1
UNET D1D2 MinQTol=1
Write IC File= 0
Write IC File at Fixed DateTime=0
Write IC File at Sim End=0
Echo Input=False
Echo Parameters=False
Echo Output=False
Write Detailed= 0
HDF Write Warmup=0
HDF Write Time Slices=0
HDF Flush=0
HDF Compression= 1
HDF Chunk Size= 1
HDF Spatial Parts= 1
HDF Use Max Rows=0
HDF Fixed Rows= 1
Calibration Method= 0
Calibration Iterations= 20
Calibration Max Change=0.05
Calibration Tolerance=0.2
Calibration Maximum=1.5
Calibration Minimum=0.5
Calibration Optimization Method= 1
WQ AD Non Conservative
WQ ULTIMATE=-1
WQ Max Comp Step=1HOUR
WQ Output Interval=15MIN
WQ Output Selected Increments= 0
WQ Output face flow=0
WQ Output face velocity=0
WQ Output face area=0
WQ Output face dispersion=0
WQ Output cell volume=0
WQ Output cell surface area=0
WQ Output cell continuity=0
WQ Output cumulative cell continuity=0
WQ Output face conc=0
WQ Output face dconc_dx=0
WQ Output face courant=0
WQ Output face peclet=0
WQ Output face adv mass=0
WQ Output face disp mass=0
WQ Output cell mass=0
WQ Output cell source sink temp=0
WQ Output nsm pathways=0
WQ Output nsm derived pathways=0
WQ Create Restart=0
WQ Fixed Restart=0
WQ System Summary=0
WQ Write To DSS=0
Sorting and Armoring Iterations= 10
XS Update Threshold= 0.02
Bed Roughness Predictor= 0
Hydraulics Update Threshold= 0.02
Energy Slope Method= 1
Volume Change Method= 1
Sediment Retention Method= 0
Sediment TS Multiplier= 1
Warm Up Method= 0
XS Weighting Method= 0
Number of US Weighted Cross Sections= 1
Number of DS Weighted Cross Sections= 1
Upstream XS Weight=0
Main XS Weight=1
Downstream XS Weight=0
Number of DS XS's Weighted with US Boundary= 1
Upstream Boundary Weight= 1
Weight of XSs Associated with US Boundary= 0
Number of US XS's Weighted with DS Boundary= 1
Downstream Boundary Weight= 0.5
Weight of XSs Associated with DS Boundary= 0.5
Percentile Method= 0
Sediment Output Level= 3
Mass or Volume Output= 0
Output Increment Type= 1
Profile and TS Output Increment= 1
Transport Output Increment 1
XS Output Flag= 0
XS Output Increment= 10
Read HDF5 Sediment Hotstart= 0
Sediment Hotstart Type= 0
Write Gradation File= 0
Read Gradation Hotstart= 0
Write HDF5 File= 1
Write Binary Output= 1
Write DSS Sediment File= 0
DSS Sediment Output Type= 1
SV Curve= 0
Specific Gage Flag= 0
Subcell Erosion Methods= 0
Subcell Deposition Methods= 0
Advection Scheme= 1
Matrix Solver= 0
Implicit Weighting Factor= 1
Maximum Outer Loop Convergence Iterations= 5
Convergence Maximum Absolute= 0.001
Convergence RMSE= 0.0001
Grain Fractions Max Abs Error= 0.001
Max Subgrid Regions= 1
Max Subgrid Length Scale= 3.402823E+38
Initial Layer Thickness= 3.402823E+38
Min Layer Thickness= 3.402823E+38
Max Layer Thickness= 3.402823E+38
Number of Layers= 5

--- DRKFK_2T2.f01 (steady flow) ---

Flow Title=Flow
Program Version=6.20
Number of Profiles= 1
Profile Names=P100yr
River Rch & RM=DRKFK_2T2,Main            ,2240
     329
Boundary for River Rch & Prof#=DRKFK_2T2,Main            , 1
Up Type= 0
Dn Type= 3
Dn Slope=0.02439
DSS Import GetInterval= 0
DSS Import GetPeak= 0
DSS Import FillOption= 0

--- DRKFK_2T2.g01 (geometry) ---

Geom Title=Geometry
Program Version=6.20

River Reach=DRKFK_2T2       ,Main
Reach XY= 30
     2385271.495      702530.377 2385285.4232729702489.485759416
2385281.26584885702438.557314725     2385383.995      702360.933
     2385408.995      702331.0722385425.38988281702286.118432654
     2385458.803      702230.257     2385487.342      702129.785
     2385474.093      702026.6522385491.97406804701963.698232075
2385493.64092773701925.115443751     2385506.031      701894.066
     2385506.464      701869.8142385494.33383174701826.723074415
     2385504.829      701802.599     2385508.441      701734.462
 2385550.1126045701643.7964159312385578.17521688701552.679538693
2385640.17190401701494.033780071     2385646.495      701418.572
2385719.06873998701343.2084920992385741.92678007701301.408300118
2385749.88793196701160.068191981     2385808.344      701061.627
     2385823.535      701013.8842385817.18787606700854.477532193
 2385824.9405079700751.4805759442385927.44021585700578.217617355
2385931.50723866700551.103701341     2385950.565       700511.56

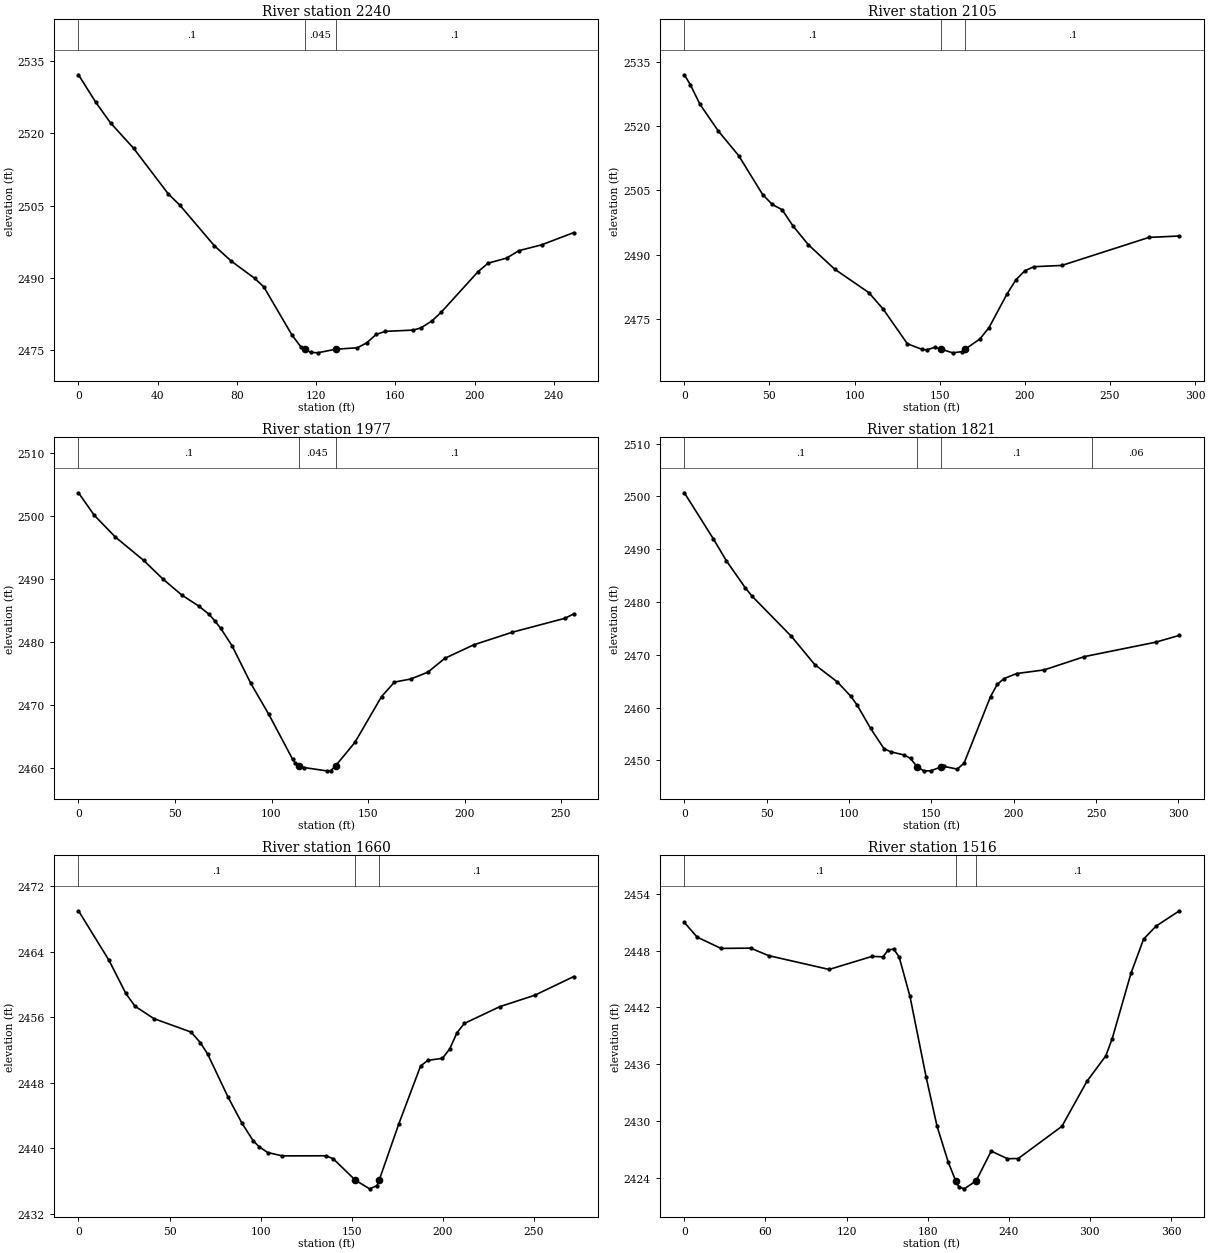
Type RM Length L Ch R = 1 ,2240    ,128.3,134.9,132.4
XS GIS Cut Line= 2
 2385375.5885191702588.1504751062385163.58853023702455.651400699
#Sta/Elev= 30
       0 2532.14     8.7 2526.46    16.2 2522.15    27.9 2516.87    45.3 2507.47
    51.2  2505.1    68.5 2496.75    77.2 2493.49    88.9 2489.97    93.6 2488.16
   107.8 2478.19   112.5 2475.63  114.192475.244   117.2 2474.63   120.7  2474.5
  129.822475.245   140.8 2475.55   145.5 2476.55   150.3 2478.32     155 2478.95
   169.1 2479.22     173 2479.68   178.6 2481.15   183.3 2482.98   201.8 2491.34
   206.9  2493.1   216.3 2494.15   222.3 2495.67     234 2496.91     250 2499.41
#Mann= 3 ,-1,0
       0      .1       0  114.19    .045       0  129.82      .1       0
Bank Sta=114.19,129.82
XS Rating Curve= 0 ,0
Exp/Cntr(USF)=0,0
Exp/Cntr=0.3,0.1

Type RM Length L Ch R = 1 ,2105    ,131.9,127.8,125.9
XS GIS Cut Line= 3
2385422.06718113 702532.232493692385277.99305751702366.298847867
2385211.42087626702391.139214008
#Sta/Elev= 30
       0 2532.06     3.5 2529.76     9.2 2525.15    19.9 2518.94    31.9 2513.16
      46 2504.04    51.7 2501.72    57.4 2500.51    63.9 2496.66    72.9 2492.29
    88.3 2486.59   108.4  2481.1   116.9 2477.19     131 2469.14   139.6 2467.84
   142.4 2467.72   147.1 2468.31   150.9 2467.87   157.7 2467.02     163  2467.3
  165.012467.877   173.6 2470.27   178.9 2472.89   189.5 2480.75   194.7 2484.08
     200  2486.2   205.3 2487.17   221.7 2487.46   272.9 2494.02   290.8 2494.35
#Mann= 3 ,-1,0
       0      .1       0   150.9    .045       0  165.01      .1       0
Bank Sta=150.9,165.01
XS Rating Curve= 0 ,0
Exp/Cntr(USF)=0,0
Exp/Cntr=0.3,0.1

Type RM Length L Ch R = 1 ,1977    ,158.8,156.2,152.9
XS GIS Cut Line= 4
2385510.31753056702406.6312293772385443.92670334702346.426554954
2385370.39921956702304.6947398362385295.25923384702338.344818249
#Sta/Elev= 30
       0 2503.67     8.2  2500.1    19.1 2496.66    33.7 2492.97    43.8 2489.99
    53.5 2487.47    62.3 2485.72    67.7  2484.4    70.5 2483.42    73.6 2482.23
    79.6 2479.41    89.3 2473.45    98.5 2468.62   110.9 2461.47   112.3 2460.85
  114.342460.436   116.9 2460.13   128.5 2459.61   130.7 2459.63  133.272460.435
   143.2 2464.11     157 2471.37   163.7 2473.67   172.1 2474.16     181 2475.24
   189.8 2477.44   204.7 2479.57   224.8 2481.58   251.9 2483.77   256.5 2484.46
#Mann= 3 ,-1,0
       0      .1       0  114.34    .045       0  133.27      .1       0
Bank Sta=114.34,133.27
XS Rating Curve= 0 ,0
Exp/Cntr(USF)=0,0
Exp/Cntr=0.3,0.1

Type RM Length L Ch R = 1 ,1821    ,161.5,160.9,159.4
XS GIS Cut Line= 4
2385602.90700025702241.7373129862385527.39033357702193.409899523
2385401.20127358702174.5312212562385332.38009395702221.475102372
#Sta/Elev= 30
       0  2500.7    17.5 2492.03    25.5 2487.82    37.1 2482.65    41.2 2481.08
      65 2473.49    79.2 2468.13    92.9 2464.85     101 2462.16     105 2460.43
   113.1 2456.04   121.2 2452.22   125.3 2451.61   133.4 2451.01   137.4 2450.34
  141.322448.752   145.5    2448   149.5    2448     156 2448.74   157.6 2448.84
   165.7 2448.33   169.8 2449.43   185.9 2462.07     190 2464.38     194 2465.47
   201.8 2466.44   218.5 2467.13   242.9 2469.65   286.3 2472.39   300.6 2473.68
#Mann= 4 ,-1,0
       0      .1       0  141.32    .045       0     156      .1       0
  247.25     .06       0
Bank Sta=141.32,156
XS Rating Curve= 0 ,0
Exp/Cntr(USF)=0,0
Exp/Cntr=0.3,0.1

Type RM Length L Ch R = 1 ,1660    ,145.3,143.8,144.3
XS GIS Cut Line= 4
2385612.55042982702084.3808195932385542.29455326702028.469868345
2385417.09910791  702027.47625372385385.69220616702074.990654947
#Sta/Elev= 30
       0 2468.98    16.8 2462.92      26  2458.9      31 2457.35    41.4 2455.83
    61.8 2454.19    66.9 2452.91    70.9 2451.52    82.2 2446.23    89.8 2443.07
    95.9 2440.95    99.1 2440.22   103.9  2439.5   111.9 2439.09   135.9  2439.1
   139.9 2438.74  152.02 2436.13   159.9 2435.07   163.9 2435.45  165.152436.133
   175.9 2442.98   187.9 2450.06   191.9 2450.74   199.9 2450.99   203.9 2452.14
   207.9 2454.12   211.9 2455.24   231.4 2457.29   250.6 2458.68   271.9 2460.95
#Mann= 3 ,-1,0
       0      .1       0  152.02    .045       0  165.15      .1       0
Bank Sta=152.02,165.15
XS Rating Curve= 0 ,0
Exp/Cntr(USF)=0,0
Exp/Cntr=0.3,0.1

Type RM Length L Ch R = 1 ,1516    ,129.5,132.5,131.9
XS GIS Cut Line= 4
2385656.56023751    701981.769982385611.84757845701884.395744726
2385439.95224476701893.338276537 2385395.2395857701967.859374961
#Sta/Elev= 30
       0 2450.97     9.5 2449.42    27.1 2448.23      49 2448.26    62.3 2447.47
   107.1 2446.01   138.9 2447.39   146.9 2447.34   150.9 2448.07   154.9 2448.16
   158.9 2447.32   166.9 2443.16   178.9 2434.62   186.9 2429.48   195.2 2425.68
  200.772423.687     203 2423.08     207 2422.86  215.752423.688     227 2426.84
     239 2426.04     247 2426.06   279.3 2429.46   297.8 2434.21   311.7 2436.88
   316.4 2438.67   330.4 2445.62   339.7 2449.21   348.8 2450.57   366.2  2452.2
#Mann= 3 ,-1,0
       0      .1       0  200.77    .045       0  215.75      .1       0
Bank Sta=200.77,215.75
XS Rating Curve= 0 ,0
Exp/Cntr(USF)=0,0
Exp/Cntr=0.3,0.1

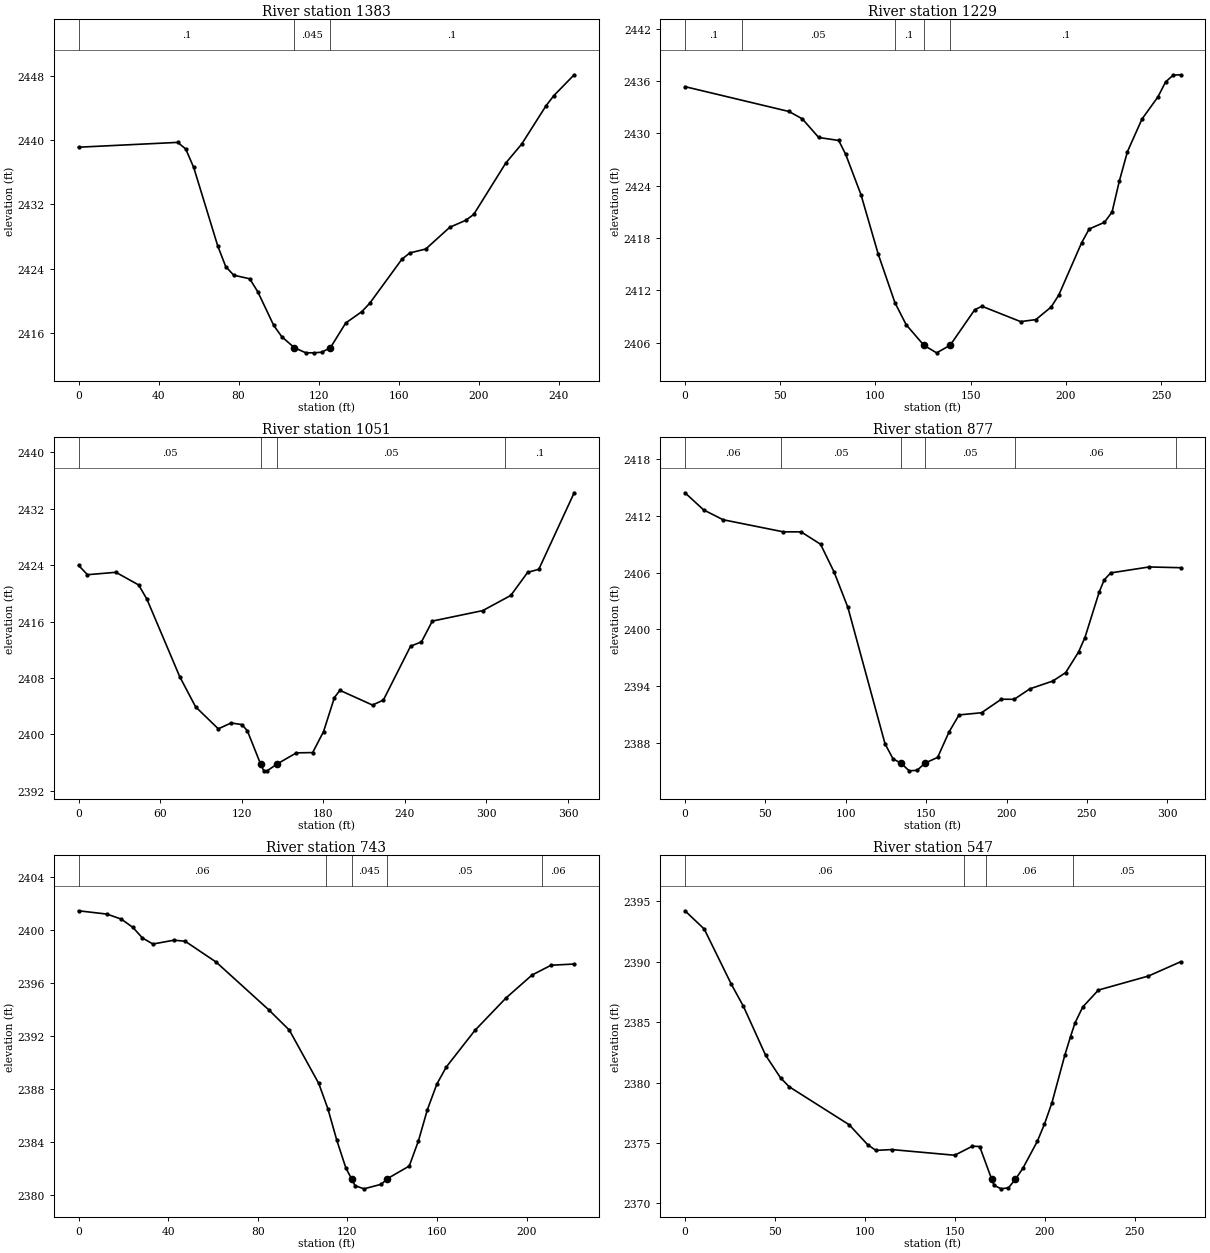
Type RM Length L Ch R = 1 ,1383    ,151.8,154.6,154.2
XS GIS Cut Line= 2
2385625.79710647701761.7511141172385378.00651817701762.836216467
#Sta/Elev= 30
       0 2439.11    49.6 2439.71    53.6 2438.89    57.6 2436.59    69.6 2426.85
    73.6 2424.27    77.6 2423.21    85.6 2422.76    89.6 2421.16    97.6 2416.97
   101.6 2415.57  107.932414.193   113.6 2413.57   117.6 2413.56   121.6 2413.64
  125.922414.193   133.6 2417.27   141.6 2418.67   145.6 2419.72   161.6 2425.17
   165.6 2425.97   173.6 2426.46   185.6 2429.16   193.6 2430.03   197.6 2430.76
   213.6 2437.14   221.6 2439.51   233.6 2444.21   237.6 2445.51   247.8 2448.11
#Mann= 3 ,-1,0
       0      .1       0  107.93    .045       0  125.92      .1       0
Bank Sta=107.93,125.92
XS Rating Curve= 0 ,0
Exp/Cntr(USF)=0,0
Exp/Cntr=0.3,0.1

Type RM Length L Ch R = 1 ,1229    ,177.6,178.2,178.3
XS GIS Cut Line= 3
2385645.62859732701706.190667519 2385578.0646805701619.100634338
 2385428.2235315701611.857309221
#Sta/Elev= 30
       0 2435.36    54.6 2432.51    61.6 2431.67    70.2 2429.53    80.7 2429.19
    84.4 2427.58    92.4 2422.97   101.5 2416.12   110.2  2410.6   116.1 2408.07
   125.42405.708   132.1 2404.84  139.212405.709   152.1 2409.78   155.9 2410.18
   176.2 2408.42   184.2 2408.65   192.2 2410.09   196.2 2411.45   208.2 2417.45
   212.2 2419.04   220.2  2419.8   224.2 2420.98     228 2424.52   232.3 2427.92
   239.9 2431.64   248.3 2434.19   252.3  2435.9   256.3 2436.68   260.2 2436.72
#Mann= 5 ,-1,0
       0      .1       0      30     .05       0     110      .1       0
   125.4    .045       0  139.21      .1       0
Bank Sta=125.4,139.21
XS Rating Curve= 0 ,0
Exp/Cntr(USF)=0,0
Exp/Cntr=0.3,0.1

Type RM Length L Ch R = 1 ,1051    ,168.9,173.2,176.5
XS GIS Cut Line= 4
2385710.92112315701571.451466797  2385680.406989701472.045666781
2385520.43503105 701470.058437492385423.06079578701494.898803631
#Sta/Elev= 30
       0 2423.97     6.6 2422.64    27.5 2422.98    44.2 2421.19    50.3 2419.17
    74.4 2408.19    86.1  2403.9   102.8 2400.78   112.2 2401.61   120.2 2401.38
   124.2 2400.49  133.942395.764   136.2 2394.84   138.7 2394.82   145.82395.762
   160.2 2397.37   172.2 2397.41   180.2 2400.39   188.2 2405.22   192.2 2406.24
   216.2 2404.15   224.2 2404.86   244.2  2412.5   252.2 2413.11   260.2 2416.06
   297.3 2417.55   317.9  2419.7   330.3 2422.97   338.5 2423.41   364.5 2434.26
#Mann= 4 ,-1,0
       0     .05       0  133.94    .045       0   145.8     .05       0
  313.97      .1       0
Bank Sta=133.94,145.8
XS Rating Curve= 0 ,0
Exp/Cntr(USF)=0,0
Exp/Cntr=0.3,0.1

Type RM Length L Ch R = 1 ,877     ,136.7,133.9,129.2
XS GIS Cut Line= 4
 2385783.3843685701448.685244984 2385771.8195364701364.735285051
2385691.33675011701304.124791667 2385568.7234756 701300.71803549
#Sta/Elev= 30
       0 2414.44    11.6 2412.63    23.7 2411.59    61.2 2410.31    72.2 2410.31
    84.3    2409    92.7 2406.07   101.3 2402.32   124.4  2387.9   129.4 2386.31
  134.322385.863   139.4 2385.05   144.4 2385.11  149.232385.864   157.1 2386.47
   164.1 2389.13   170.4 2390.96   184.4 2391.19   196.7 2392.62   204.7 2392.61
   214.5 2393.72   228.7 2394.54   236.7 2395.43   244.7  2397.6   248.7 2399.14
   257.6 2403.97   260.7 2405.24   264.7 2405.97   288.6  2406.6   308.2 2406.52
#Mann= 6 ,-1,0
       0     .06       0      60     .05       0  134.32    .045       0
  149.23     .05       0   205.5     .06       0   305.5     .05       0
Bank Sta=134.32,149.23
XS Rating Curve= 0 ,0
Exp/Cntr(USF)=0,0
Exp/Cntr=0.3,0.1

Type RM Length L Ch R = 1 ,743     ,196.6,196.6,196.2
XS GIS Cut Line= 4
2385864.49058001701258.3092299832385778.77483892701205.756941747
2385723.13241877701197.8080245822385662.52192538701175.948502378
#Sta/Elev= 30
       0 2401.45    12.7  2401.2    19.1 2400.82    24.3 2400.19    28.5  2399.4
    33.2 2398.94    42.6 2399.23    47.6 2399.15    61.4 2397.58    84.8 2393.99
    94.1 2392.44   107.2 2388.42   111.3  2386.5   115.3 2384.11   119.3 2382.04
  121.842381.217   123.4  2380.7   127.4 2380.46   135.2 2380.81  137.712381.216
   147.6 2382.18   151.7 2384.08   155.7 2386.44   159.9 2388.36   164.1 2389.65
   176.9 2392.42   190.8 2394.87   202.4  2396.6   210.9 2397.34   221.2 2397.43
#Mann= 5 ,-1,0
       0     .06       0  110.54     .05       0  121.84    .045       0
  137.71     .05       0  206.75     .06       0
Bank Sta=121.84,137.71
XS Rating Curve= 0 ,0
Exp/Cntr(USF)=0,0
Exp/Cntr=0.3,0.1

Type RM Length L Ch R = 1 ,547     ,319.3,322.5,324.2
XS GIS Cut Line= 4
 2385905.4167444701170.0658340052385840.27322577701024.265719905
2385798.64713184701022.9318469482385729.46864287701049.596203663
#Sta/Elev= 30
       0 2394.22    10.7 2392.71    25.8 2388.13    32.5 2386.31    44.8 2382.27
    53.1  2380.4    57.9 2379.66    91.3 2376.51   101.5 2374.87   106.1 2374.39
   114.9 2374.46   149.9 2373.99   159.8 2374.74   163.8 2374.71   170.5    2372
   171.8  2371.5   175.8 2371.21   179.8  2371.3   183.72372.002   187.8 2372.91
   195.8 2375.13   199.8 2376.56     204 2378.35   211.2 2382.31   214.3 2383.81
   216.8 2384.94   221.1 2386.26   229.8 2387.66   257.6 2388.82   275.5    2390
#Mann= 4 ,-1,0
       0     .06       0  155.02    .045       0   167.3     .06       0
  215.54     .05       0
Bank Sta=170.5,183.7
XS Rating Curve= 0 ,0
Exp/Cntr(USF)=0,0
Exp/Cntr=0.3,0.1

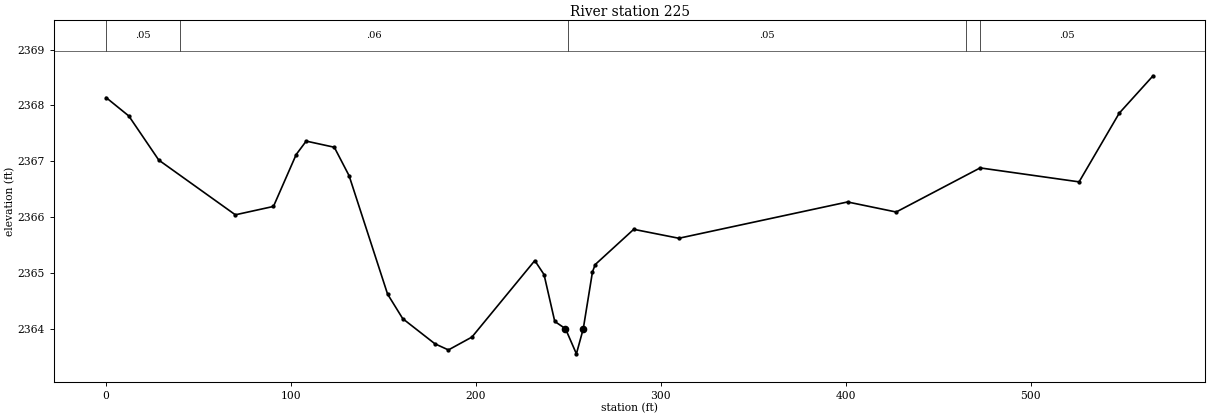
Type RM Length L Ch R = 1 ,225     ,,,
XS GIS Cut Line= 4
2385922.61895672700945.143506699 2385868.7342691 700720.41383404
2385840.66167211700703.4967434692385610.24942967700899.049830508
#Sta/Elev= 30
       0 2368.14    12.3 2367.81    28.5 2367.02    69.9 2366.04    90.5 2366.19
   102.8 2367.12   108.2 2367.36   123.4 2367.25   131.4 2366.74   152.2 2364.62
   160.4 2364.18   177.8 2363.73   185.1 2363.62   197.8 2363.85   231.8 2365.22
   236.8 2364.97   242.6 2364.13   248.4    2364   254.3 2363.55  258.02    2364
     263 2365.02   264.5 2365.15   285.3 2365.78   309.7 2365.62   400.9 2366.27
   427.2 2366.09   472.6 2366.88   526.1 2366.63   547.8 2367.86   566.1 2368.53
#Mann= 5 ,-1,0
       0     .05       0      40     .06       0     250     .05       0
  464.76    .045       0   472.6     .05       0
Bank Sta=248.4,258.02
XS Rating Curve= 0 ,0
Exp/Cntr(USF)=0,0
Exp/Cntr=0.3,0.1
LCMann Table=0

Chan Stop Cuts=-1
Use User Specified Reach Order=0
Composite Channel Slope=5